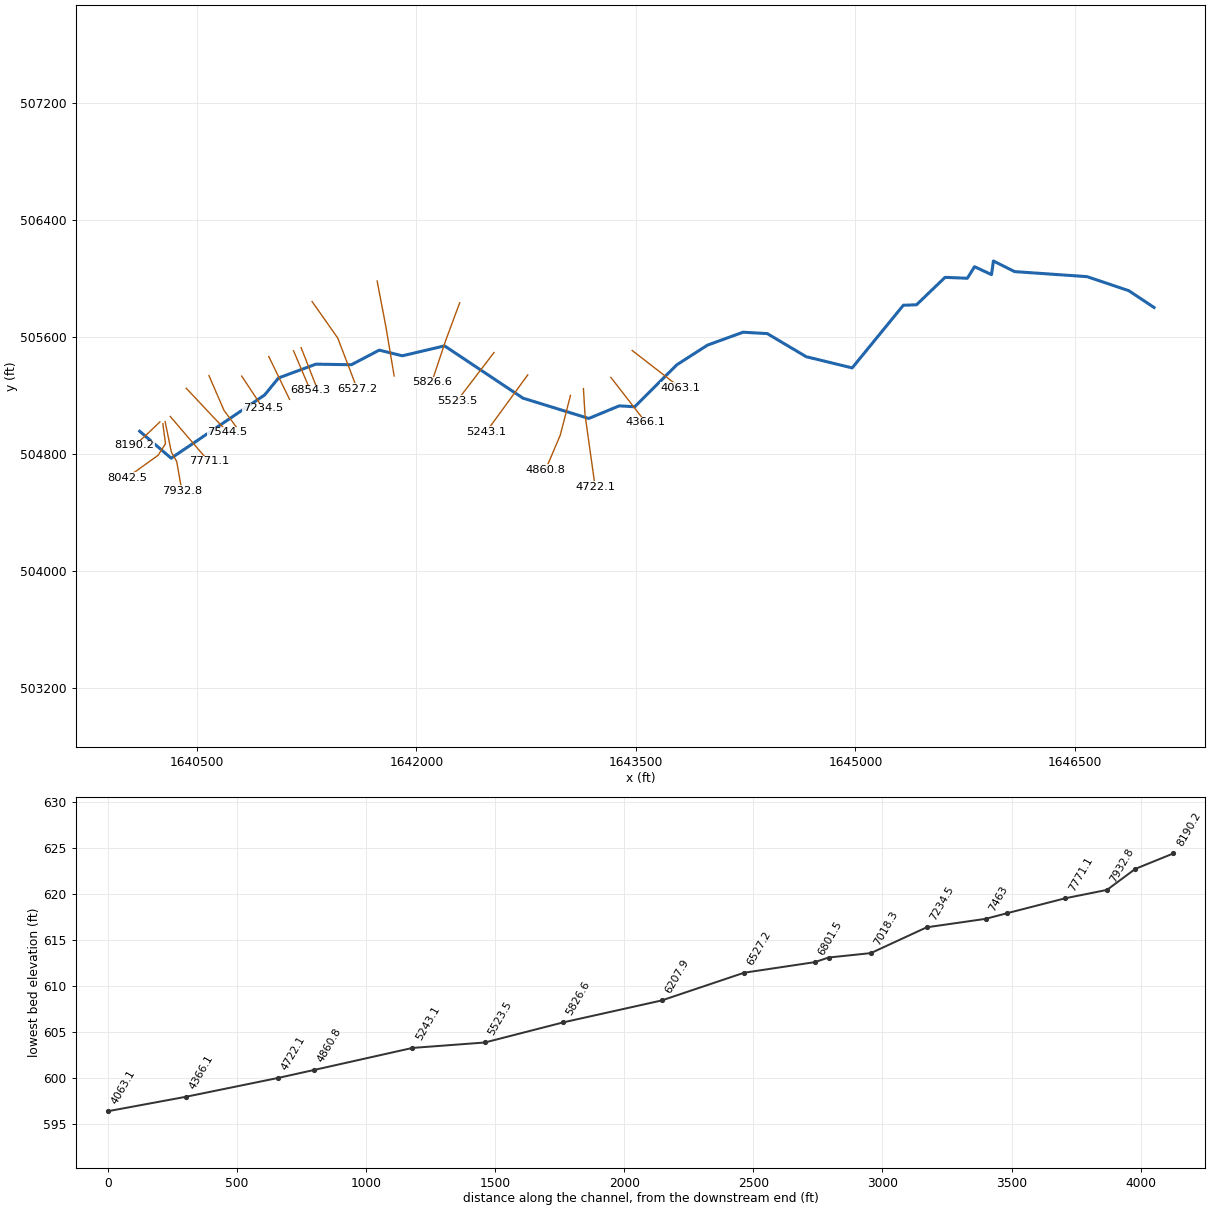
--- BTMileCr.prj (project) ---

Proj Title=BTMileCr
Current Plan=p01
Default Exp/Contr=0,0
English Units
Geom File=g01
Flow File=f01
Plan File=p01
BEGIN DESCRIPTION:
END DESCRIPTION:
DSS Export Rating Curves= 0
DSS Export Rating Curve Sorted= 0
DSS Export Volume Flow Curves= 0
DXF OffsetX= 0
DXF OffsetY= 0
DXF ScaleX= 0
DXF ScaleY= 0

--- BTMileCr.p01 (plan) ---

Plan Title=Floodplain
Program Version=4.00
Geom File=g01
Flow File=f01
K Sum by GR=0
Std Step Tol=0.01
Critical Tol=0.01
Num of Std Step Trials=20
Max Error Tol=0.3
Flow Tol Ratio=0.001
Split Flow NTrial=30
Split Flow Tol=0.02
Split Flow Ratio=0.02
Log Output Level=0
Friction Slope Method=1
Unsteady Friction Slope Method=2
Unsteady Bridges Friction Slope Method=1
Global Log Level=0
CheckData=False
Run HTab=0
Run UNet=0
Run PostProcess=0
UNET Theta=0
UNET Theta Warmup=0
UNET ZTol=0
UNET ZSATol=0
UNET MxIter=0
UNET MaxInSteps=0
UNET DtIC=0
UNET DtMin=0
UNET MaxCRTS=0
UNET WFStab=0
UNET SFStab=0
UNET WFX=0
UNET SFX=0
UNET DSS MLevel=0
UNET DZMax Abort=0
UNET Convert EG Bridges=0
UNET Use Existing IB Tables=0
UNET Froude Limit=0
UNET Froude Power=0
Write IC File=0
Echo Input=False
Echo Output=False
Write Detailed=0

--- BTMileCr.f01 (steady flow) ---

Flow Title=NFF Regression Equation
Program Version=4.10
Number of Profiles= 1
Profile Names=P100yr
River Rch & RM=BTMileCr,Main            ,8190.2
     761
River Rch & RM=BTMileCr,Main            ,7771.1
     900
River Rch & RM=BTMileCr,Main            ,7234.5
    1046
River Rch & RM=BTMileCr,Main            ,6527.2
    1052
River Rch & RM=BTMileCr,Main            ,6207.9
    1227
River Rch & RM=BTMileCr,Main            ,5243.1
    1262
Boundary for River Rch & Prof#=BTMileCr,Main            , 1
Up Type= 0
Dn Type= 3
Dn Slope=0.004
DSS Import GetInterval= 0
DSS Import GetPeak= 0
DSS Import FillOption= 0

--- BTMileCr.g01 (geometry) ---

Geom Title=USGS 10m DEM
Program Version=4.10

River Reach=BTMileCr        ,Main
Reach XY= 30
     1640108.465      504956.328     1640323.956      504771.809
     1640962.412      505204.172     1641057.788      505320.914
     1641313.192      505415.216     1641555.443      505411.223
     1641745.519      505511.064     1641903.765      505472.479
     1642192.144      505540.241     1642728.675      505182.348
     1643177.723      505043.746     1643386.215      505129.957
     1643491.612      505123.607     1643779.112       505410.76
     1643988.835      505545.482      1644231.89      505633.677
     1644397.168      505624.302     1644663.835      505465.968
     1644977.723      505389.579     1645327.213       505818.29
     1645417.318      505821.415     1645612.261        506009.1
     1645764.345       506002.85      1645813.65      506082.016
     1645929.622       506027.85     1645942.817      506120.905
     1646087.131      506048.423     1646582.791      506013.917
     1646868.381      505917.563     1647040.532      505802.877

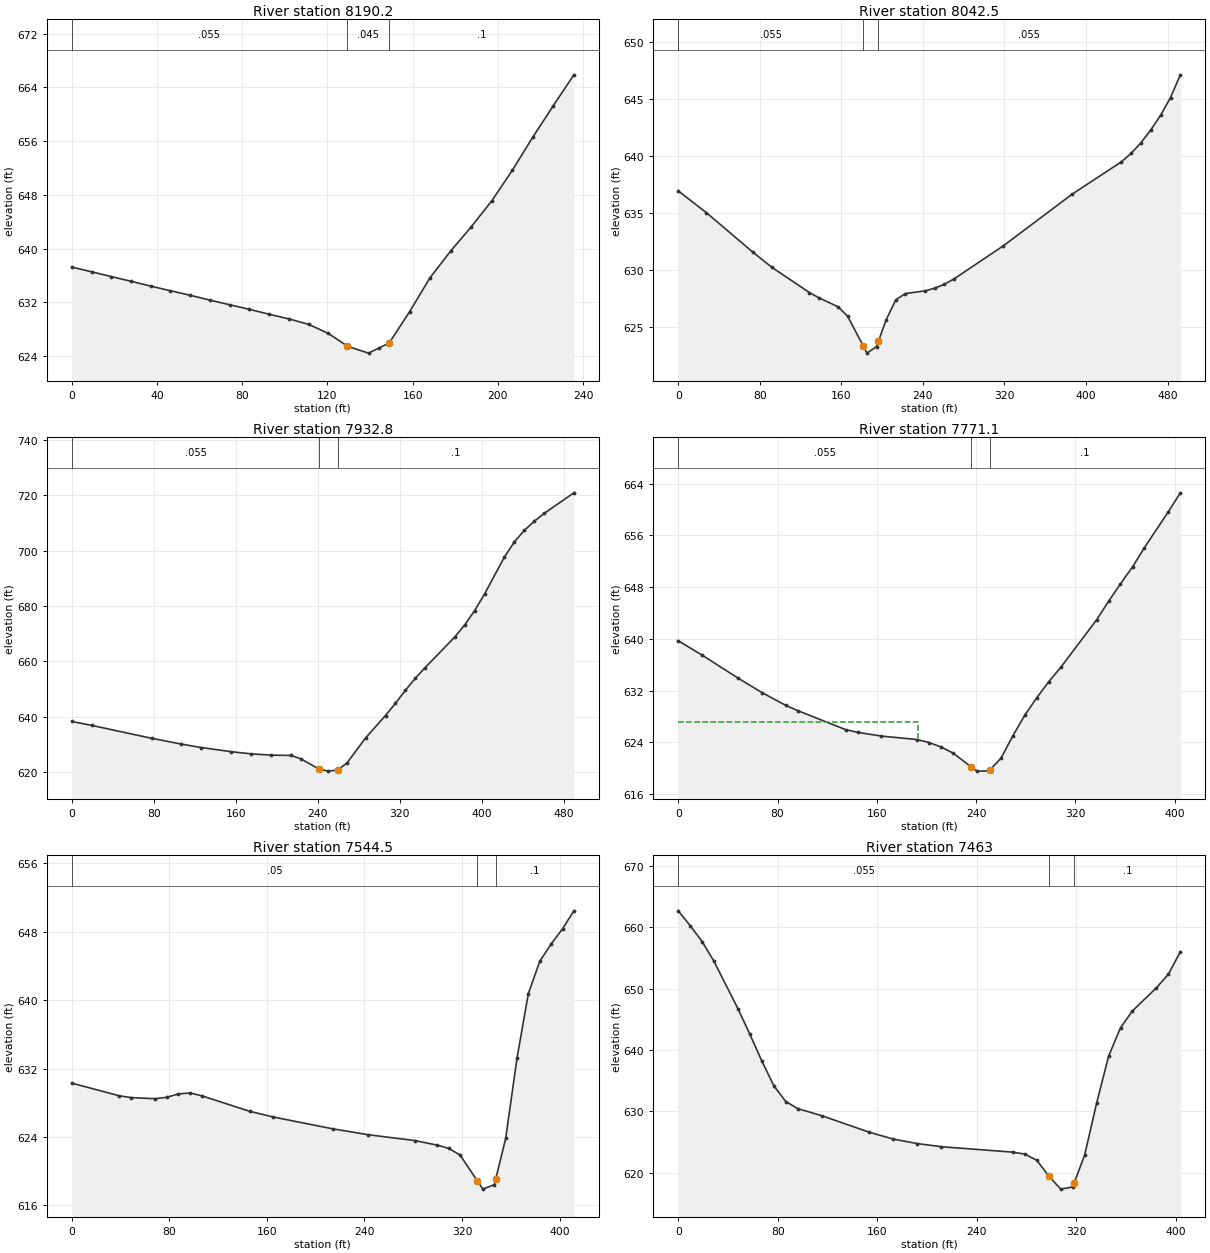
Type RM Length L Ch R = 1 ,8190.2  ,142,147.7,153.8
XS GIS Cut Line= 3
     1640246.853       505020.11      1640153.12      504930.493
     1640074.327      504859.519
#Sta/Elev= 28
       0  637.23     9.3  636.53    18.5  635.82    27.8  635.12      37   634.4
    46.3  633.71    55.6  633.03    64.8  632.31    74.1  631.62    83.4  630.94
    92.6  630.21   101.9  629.51   111.2   628.7   120.4  627.35   129.2   625.5
   129.7   625.4   139.3  624.41   144.2  625.17     149  625.91   158.6  630.59
   168.2  635.65   177.9  639.64   187.5  643.21   197.2  647.12   206.8  651.64
   216.4  656.58   226.1   661.3   235.7  665.88
#Mann= 3 , 0 , 0
       0    .055       0   129.2    .045       0     149      .1       0
Bank Sta=129.2,149
XS Rating Curve= 0 ,0
Exp/Cntr=0.3,0.1

Type RM Length L Ch R = 1 ,8042.5  ,83.4,109.6,135.6
XS GIS Cut Line= 4
     1640266.963       505007.74     1640285.192      504871.021
     1640234.411      504791.594      1640023.04      504639.684
#Sta/Elev= 28
       0  636.95    27.6  635.04    73.6  631.55      92  630.24   128.7  628.04
   137.9  627.58   156.8  626.79   166.2  625.96   181.3  623.39   185.1  622.73
   194.5   623.3   196.3  623.75   203.9  625.64   213.4   627.4   222.8  627.95
   241.8  628.18   251.5  628.42   261.1  628.76   270.8  629.25     319  632.14
   386.4  636.66   434.6  639.49   444.3  640.24   453.9  641.17   463.6   642.3
   473.2  643.58   482.9  645.13   492.5  647.12
#Mann= 3 , 0 , 0
       0    .055       0   181.3    .045       0   196.3    .055       0
Bank Sta=181.3,196.3
XS Rating Curve= 0 ,0
Exp/Cntr=0.3,0.1

Type RM Length L Ch R = 1 ,7932.8  ,157.5,161.8,165.9
XS GIS Cut Line= 4
     1640282.588      505022.063     1640325.557      504812.427
     1640361.855      504749.419     1640396.593      504549.406
#Sta/Elev= 30
       0  638.36    19.4  636.95    77.8   632.3     107  630.19   126.4  628.96
   155.6  627.45   175.1  626.67   194.5  626.22     214   626.1   223.1  624.95
   241.3  621.16   250.4  620.45   259.4  620.85   268.5  623.43   286.7  632.47
     306  640.51   315.7  644.91   325.4  649.58     335  653.94   344.7   657.8
   373.7  668.88   383.4  673.25     393  678.38   402.7   684.4     422  697.68
   431.7  703.14   441.4  707.28     451  710.55   460.7  713.38   489.7  720.82
#Mann= 3 , 0 , 0
       0    .055       0   241.3    .045       0   259.4      .1       0
Bank Sta=241.3,259.4
XS Rating Curve= 0 ,0
Exp/Cntr=0.3,0.1

Type RM Length L Ch R = 1 ,7771.1  ,225.5,226.6,227.8
XS GIS Cut Line= 2
     1640317.744      505057.219     1640580.765      504749.927
#Sta/Elev= 30
       0   639.7    19.3  637.47    48.2  633.92    67.4  631.69    86.7   629.7
    96.3  628.89   134.8  625.96   144.5  625.54   163.7  624.96   192.6  624.42
   202.2  623.96   211.9  623.26   221.5  622.32   235.8  620.22   240.8  619.54
   250.4  619.58   250.8  619.66     260  621.53   269.7  625.04   279.3  628.21
   288.9   630.9   298.6  633.38   308.2  635.59   337.1  642.94   346.7   645.8
   356.3   648.5     366  651.12   375.6   654.1   394.8  659.62   404.5  662.57
#Mann= 3 , 0 , 0
       0    .055       0   235.8    .045       0   250.8      .1       0
#XS Ineff= 2 , 0
          192.84  627.21
Permanent Ineff=
       F       F
Bank Sta=235.8,250.8
XS Rating Curve= 0 ,0
Exp/Cntr=0.3,0.1

Type RM Length L Ch R = 1 ,7544.5  ,84.5,81.4,78.1
XS GIS Cut Line= 3
     1640427.119      505249.927     1640606.807      505058.521
     1640709.672      504950.448
#Sta/Elev= 27
       0   630.3    38.9  628.82    48.6  628.61    68.1  628.48    77.8  628.64
    87.5  629.04    97.2  629.15     107   628.8   145.8  627.01   165.3  626.34
   213.9  624.96   243.1  624.27   281.2  623.59   299.8  623.05   309.2  622.67
   318.5  621.88   332.6  618.87   337.1  617.91   346.5  618.43   347.6  619.07
   355.8  623.83   365.1  633.22   374.4  640.77   383.8  644.55   393.1  646.57
   402.4  648.33   411.7  650.44
#Mann= 3 , 0 , 0
       0     .05       0   332.6    .045       0   347.6      .1       0
Bank Sta=332.6,347.6
XS Rating Curve= 0 ,0
Exp/Cntr=0.3,0.1

Type RM Length L Ch R = 1 ,7463    ,229.7,228.5,227.3
XS GIS Cut Line= 3
     1640582.067      505337.167     1640684.932      505098.886
     1640770.869         504983.
#Sta/Elev= 30
       0   662.7     9.6  660.29    19.2  657.69    28.8  654.45    48.1  646.71
    57.7  642.53    67.3  638.18    76.9  634.17    86.5  631.59    96.1  630.44
   115.4  629.29   153.8  626.58     173  625.47   192.2  624.74   211.5  624.23
   269.2  623.34   278.8  623.02   288.4  622.01     298  619.44   307.6  617.31
   317.2  617.66  318.56  618.37   326.9   622.9   336.5  631.34   346.1  638.97
   355.7  643.63   365.3  646.38   384.6  650.14   394.2  652.36   403.8  656.01
#Mann= 3 , 0 , 0
       0    .055       0     298    .045       0  318.56      .1       0
Bank Sta=298,318.56
XS Rating Curve= 0 ,0
Exp/Cntr=0.3,0.1

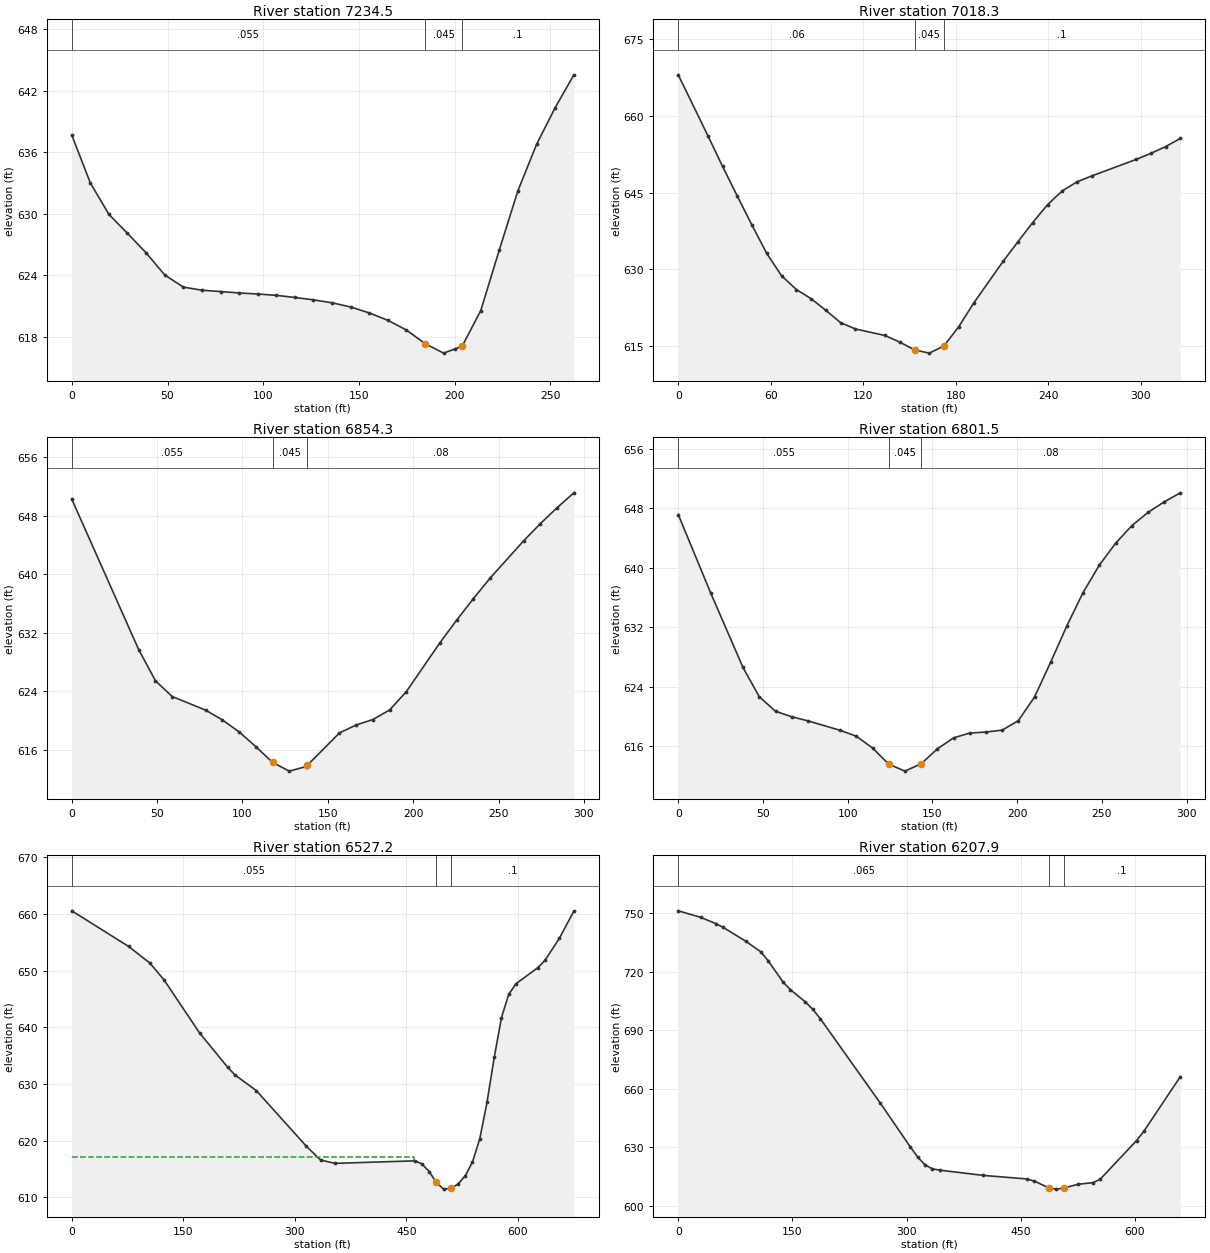
Type RM Length L Ch R = 1 ,7234.5  ,219.1,216.2,213.3
XS GIS Cut Line= 2
     1640806.026      505333.261     1640950.557      505114.511
#Sta/Elev= 30
       0  637.67     9.7     633    19.4  629.93    29.1  628.08    38.8  626.18
    48.6  624.01    58.3  622.83      68  622.53    77.7   622.4    87.4  622.26
    97.1  622.16   106.8  622.03   116.5  621.82   126.2  621.59     136   621.3
   145.7  620.89   155.4  620.31   165.1  619.59   174.8  618.64   184.5  617.32
   185.1  617.26   194.2  616.39   200.1   616.8   203.9  617.07   213.6  620.55
   223.3  626.48     233  632.24   242.8  636.79   252.5  640.36   262.2  643.55
#Mann= 3 , 0 , 0
       0    .055       0   184.5    .045       0   203.9      .1       0
Bank Sta=184.5,203.9
XS Rating Curve= 0 ,0
Exp/Cntr=0.3,0.1

Type RM Length L Ch R = 1 ,7018.3  ,164.5,164,162.2
XS GIS Cut Line= 2
     1640990.922      505467.375     1641132.849      505174.406
#Sta/Elev= 30
       0  668.04    19.2  656.14    28.7  650.15    38.3   644.3    47.9  638.58
    57.4   633.1      67  628.72    76.6  626.03    86.2  624.23    95.8  621.94
   105.3  619.54   114.9  618.32     134  617.04   143.6  615.75   153.2  614.22
   162.8  613.59   172.3     615   181.9  618.78   191.5  623.36   210.6  631.54
   220.2  635.37   229.8  639.14   239.4  642.62   248.9  645.32   258.5   647.1
   268.1  648.26   296.8  651.48   306.4  652.67     316     654   325.5  655.59
#Mann= 3 , 0 , 0
       0     .06       0   153.2    .045       0   172.3      .1       0
Bank Sta=153.2,172.3
XS Rating Curve= 0 ,0
Exp/Cntr=0.3,0.1

Type RM Length L Ch R = 1 ,6854.3  ,53.3,52.8,52.1
XS GIS Cut Line= 2
     1641160.192      505506.872     1641274.776      505236.038
#Sta/Elev= 25
       0  650.29    39.2  629.72      49  625.47    58.8  623.31    78.4  621.45
    88.2  620.11      98  618.48   107.8  616.46   117.6  614.31   127.4  613.11
   137.2  613.73   137.9  613.89   156.8  618.33   166.6  619.42   176.4  620.16
   186.2  621.47     196  623.98   215.6  630.64   225.5  633.76   235.3   636.7
   245.1  639.51   264.7  644.59   274.5  646.94   284.3  649.12   294.1  651.15
#Mann= 3 , 0 , 0
       0    .055       0   117.6    .045       0   137.9     .08       0
Bank Sta=117.6,137.9
XS Rating Curve= 0 ,0
Exp/Cntr=0.3,0.1

Type RM Length L Ch R = 1 ,6801.5  ,273.5,274.3,274.4
XS GIS Cut Line= 2
     1641212.276      505527.705     1641319.915      505251.663
#Sta/Elev= 29
       0  647.15    19.1  636.62    38.2  626.57    47.8  622.63    57.4  620.67
    66.9  619.93    76.5  619.38    95.6   618.1   105.1  617.31   114.7  615.72
   124.2  613.55   133.8  612.61   143.4  613.61   152.9   615.6   162.5  617.09
     172  617.73   181.6  617.87   191.2  618.13   200.7   619.4   210.3   622.6
   219.8  627.28   229.4  632.19   238.9  636.64   248.5  640.34   258.1  643.28
   267.6  645.63   277.2  647.43   286.7  648.84   296.3  650.07
#Mann= 3 , 0 , 0
       0    .055       0   124.2    .045       0   143.4     .08       0
Bank Sta=124.2,143.4
XS Rating Curve= 0 ,0
Exp/Cntr=0.3,0.1

Type RM Length L Ch R = 1 ,6527.2  ,323.8,319.2,315.3
XS GIS Cut Line= 3
     1641286.928      505843.677     1641462.276      505593.677
      1641594.22      505248.191
#Sta/Elev= 30
       0  660.58    76.3  654.31     105  651.37     124  648.41   171.8  639.04
   209.9  632.93   219.5  631.61   248.1  628.86   315.1  619.08   334.6   616.6
     354  616.01   461.1  616.45   470.8  615.93   480.5  614.57   490.3  612.65
     500  611.46   509.7  611.59   519.5  612.36   529.2  613.81   538.9  616.25
   548.7  620.36   558.4  626.75   568.1   634.7   577.9  641.74   587.6  645.83
   597.3   647.7   626.5  650.52   636.3  651.83   655.7  655.72   675.2  660.54
#Mann= 3 , 0 , 0
       0    .055       0   490.3    .045       0   509.7      .1       0
#XS Ineff= 2 , 0
          460.56  617.05
Permanent Ineff=
       F       F
Bank Sta=490.3,509.7
XS Rating Curve= 0 ,0
Exp/Cntr=0.3,0.1

Type RM Length L Ch R = 1 ,6207.9  ,392.9,381.4,369.2
XS GIS Cut Line= 3
     1641731.373      505984.302     1641790.401      505675.275
     1641847.692      505334.997
#Sta/Elev= 30
       0  751.26    29.5  747.93    49.2  744.72      59  742.78    88.5  735.71
   108.2  730.31     118  725.75   137.6  714.77   147.5  710.77   167.1   704.5
     177  700.64   186.8  695.86   265.5   652.6   304.8  630.19   314.6  624.93
   324.2   620.9   333.8  618.88   343.4   618.2   400.9  615.49   458.4  613.66
     468  612.57   487.2  609.02   496.7  608.45   506.3  608.99   525.5  610.96
   544.7  611.77   554.2  613.43   602.2  633.37   611.8  638.15   659.7  666.14
#Mann= 3 , 0 , 0
       0    .065       0   487.2    .045       0   506.3      .1       0
Bank Sta=487.2,506.3
XS Rating Curve= 0 ,0
Exp/Cntr=0.3,0.1

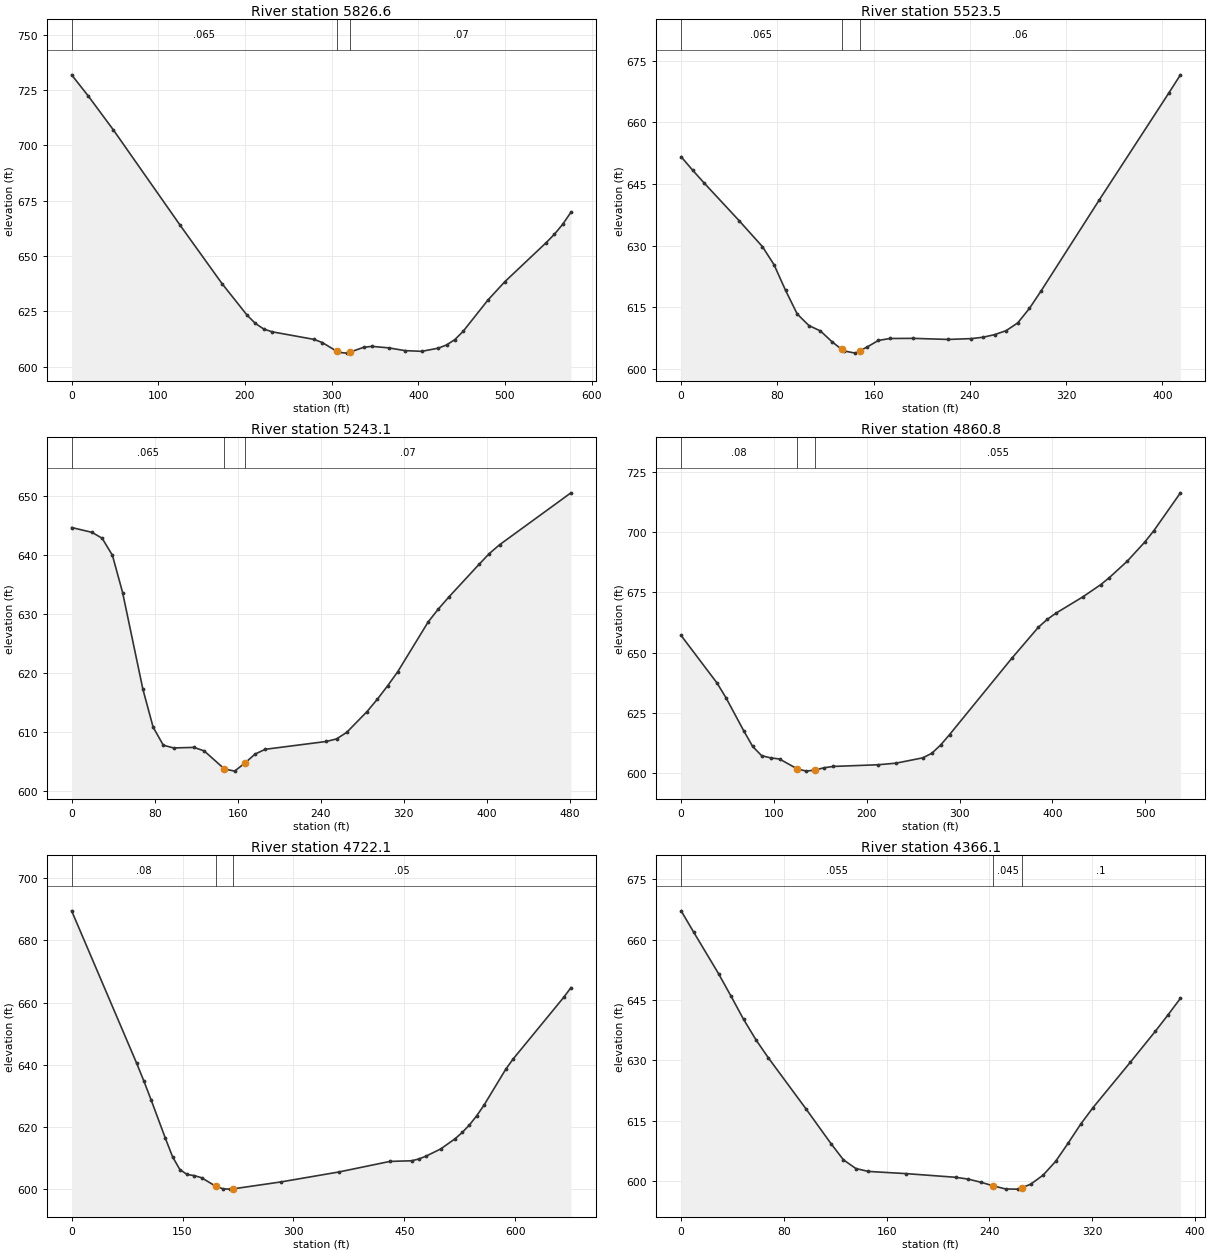
Type RM Length L Ch R = 1 ,5826.6  ,310.4,303.1,295.8
XS GIS Cut Line= 3
     1642295.609      505834.997     1642198.387      505572.844
     1642104.637      505291.594
#Sta/Elev= 30
       0   731.8    19.3  722.19    48.2  706.89   125.3  663.79   173.5  637.49
   202.5  623.19   212.1  619.46   221.8  616.93   231.4   615.7   279.6  612.28
   289.2  610.86   306.2  606.84   308.3  606.38   317.8  606.07   321.2  606.52
     337  608.71   346.5  609.13   365.7  608.45   384.8   607.2   403.9  606.88
     423  608.31   432.6  609.77   442.2   612.2   451.7  615.91   480.4  630.09
   499.6  638.25   547.4  655.93   556.9  659.73   566.5  664.23   576.1  669.72
#Mann= 3 , 0 , 0
       0    .065       0   306.2    .045       0   321.2     .07       0
Bank Sta=306.2,321.2
XS Rating Curve= 0 ,0
Exp/Cntr=0.3,0.1

Type RM Length L Ch R = 1 ,5523.5  ,279.8,280.3,280.8
XS GIS Cut Line= 2
     1642529.984      505494.719     1642278.248      505164.858
#Sta/Elev= 30
       0  651.64     9.6  648.36    19.3   645.2    48.2   636.1    67.6  629.78
    77.2   625.4    86.8  619.16    96.5   613.4   106.2   610.6   115.8  609.28
   125.4  606.66   133.3  604.85   135.1  604.44   144.8  603.89   148.3  604.42
   154.4  605.35     164  606.98   173.7  607.45     193  607.48     222  607.22
   241.2  607.42   250.9  607.75   260.6  608.39   270.2  609.36   279.8  611.25
   289.5  614.76   299.2  619.02   347.4  641.07   405.3  667.11     415  671.55
#Mann= 3 , 0 , 0
       0    .065       0   133.3    .045       0   148.3     .06       0
Bank Sta=133.3,148.3
XS Rating Curve= 0 ,0
Exp/Cntr=0.3,0.1

Type RM Length L Ch R = 1 ,5243.1  ,373.6,382.3,390.9
XS GIS Cut Line= 2
     1642760.887      505341.941     1642477.901      504953.052
#Sta/Elev= 30
       0   644.6    19.6  643.78    29.4  642.78    39.3  639.89    49.1  633.58
    68.7  617.14    78.5  610.76    88.3   607.7    98.2  607.23   117.8  607.32
   127.6  606.74   147.2  603.67     157   603.3   166.9  604.66   176.7  606.19
   186.5     607   245.4  608.33   255.2  608.76     265  609.87   284.6   613.4
   294.5  615.49   304.3  617.74   314.1  620.14   343.5   628.6   353.4  630.81
   363.2  632.78   392.6  638.38   402.4  640.19   412.2  641.67     481  650.48
#Mann= 3 , 0 , 0
       0    .065       0   147.2    .045       0   166.9     .07       0
Bank Sta=147.2,166.9
XS Rating Curve= 0 ,0
Exp/Cntr=0.3,0.1

Type RM Length L Ch R = 1 ,4860.8  ,129.6,138.7,147.4
XS GIS Cut Line= 3
     1643052.553      505201.316     1642983.109      504930.483
     1642882.415      504692.636
#Sta/Elev= 30
       0  657.08    38.6  637.44    48.2  631.39    67.5  617.57    77.1  611.11
    86.8  607.28    96.4   606.4     106  605.92   125.3   601.8     135   600.9
   144.6  601.39   154.3  602.32   163.9  602.84   212.1  603.54   231.4  604.19
   260.3   606.4     270  608.27   279.6  611.74   289.2  616.03   356.1  647.57
   384.8  660.47   394.4  663.75     404  666.37   432.6  673.04   451.8  678.07
   461.4  681.08   480.5  687.82   499.6  695.82   509.2  700.46   537.9  716.17
#Mann= 3 , 0 , 0
       0     .08       0   125.3    .045       0   144.6    .055       0
Bank Sta=125.3,144.6
XS Rating Curve= 0 ,0
Exp/Cntr=0.3,0.1

Type RM Length L Ch R = 1 ,4722.1  ,341.4,356,368.6
XS GIS Cut Line= 3
     1643141.095      505248.191     1643151.512      505072.844
     1643220.956      504578.052
#Sta/Elev= 30
       0  689.52    87.8   640.6    97.6  634.86   107.4   628.8   126.9  616.32
   136.6   610.4   146.4  606.33   156.1  604.76   165.9  604.38   175.7  603.71
   194.7  600.99     205  600.11   214.8  600.04  218.51  600.13   283.4  602.37
   361.8  605.57   430.4  608.95   459.8  609.16   469.6  609.73   479.4  610.66
     499  612.94   518.6  616.23   528.3  618.27   538.1   620.7   547.9  623.64
   557.7  627.03   587.1  638.57   596.9  641.82   665.5   661.7   675.3  664.82
#Mann= 3 , 0 , 0
       0     .08       0   194.7    .045       0  218.51     .05       0
Bank Sta=194.7,218.51
XS Rating Curve= 0 ,0
Exp/Cntr=0.3,0.1

Type RM Length L Ch R = 1 ,4366.1  ,300,303,307.8
XS GIS Cut Line= 2
     1643328.595       505324.58     1643566.442      505017.288
#Sta/Elev= 30
       0  667.16     9.7   661.9    29.1  651.56    38.9  645.92    48.6   640.2
    58.3  635.08      68  630.58    97.2  617.94   116.6  609.33   126.3  605.29
     136  603.12   145.7   602.4   174.9  601.86   213.7  600.94   223.4  600.49
   233.2  599.72   242.9  598.82   252.6  598.03   262.3     598  265.12  598.35
     272  599.21   281.7  601.47   291.4  604.87   301.2  609.42   310.9  614.12
   320.6  618.27   349.7  629.57   369.2  637.28   378.9  641.29   388.6  645.42
#Mann= 3 , 0 , 0
       0    .055       0   242.9    .045       0  265.12      .1       0
Bank Sta=242.9,265.12
XS Rating Curve= 0 ,0
Exp/Cntr=0.3,0.1

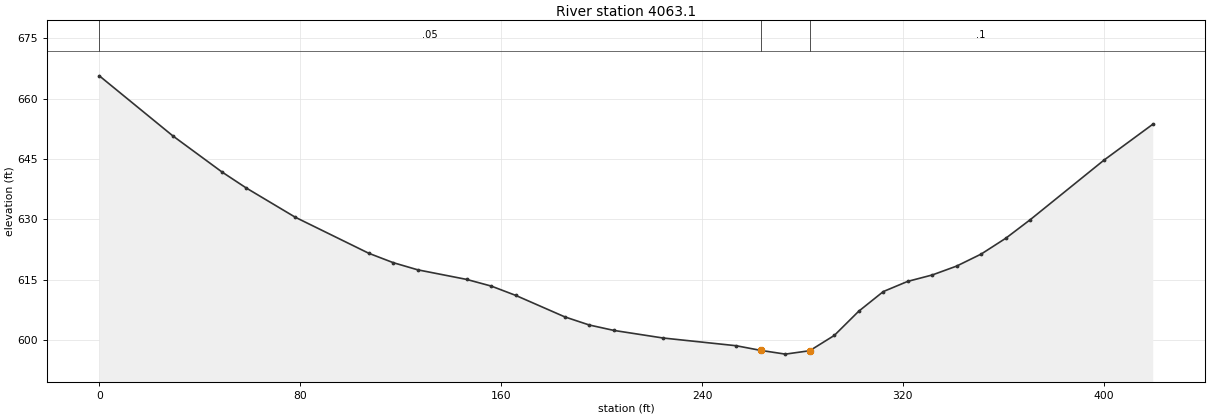
Type RM Length L Ch R = 1 ,4063.1  ,4085.2,4063.2,4026.1
XS GIS Cut Line= 2
     1643474.428      505508.608     1643806.026      505251.663
#Sta/Elev= 30
       0  665.69    29.3  650.73    48.8  641.78    58.5  637.78      78  630.51
   107.3  621.53   117.1  619.18   126.8  617.41   146.3  615.02   156.1  613.36
   165.8  611.05   185.4  605.69   195.1  603.68   204.9  602.33   224.4  600.45
   253.6  598.52   263.4  597.36   273.2  596.43   282.9  597.28   292.7  601.09
   302.4   607.1   312.2     612   321.9  614.53   331.7  616.13   341.4  618.34
   351.2  621.34     361  625.28   370.7  629.88     400  644.67   419.5  653.63
#Mann= 3 , 0 , 0
       0     .05       0   263.4    .045       0   282.9      .1       0
Bank Sta=263.4,282.9
XS Rating Curve= 0 ,0
Exp/Cntr=0.3,0.1

Chan Stop Cuts=-1
Use User Specified Reach Order=0
Composite Channel Slope=5